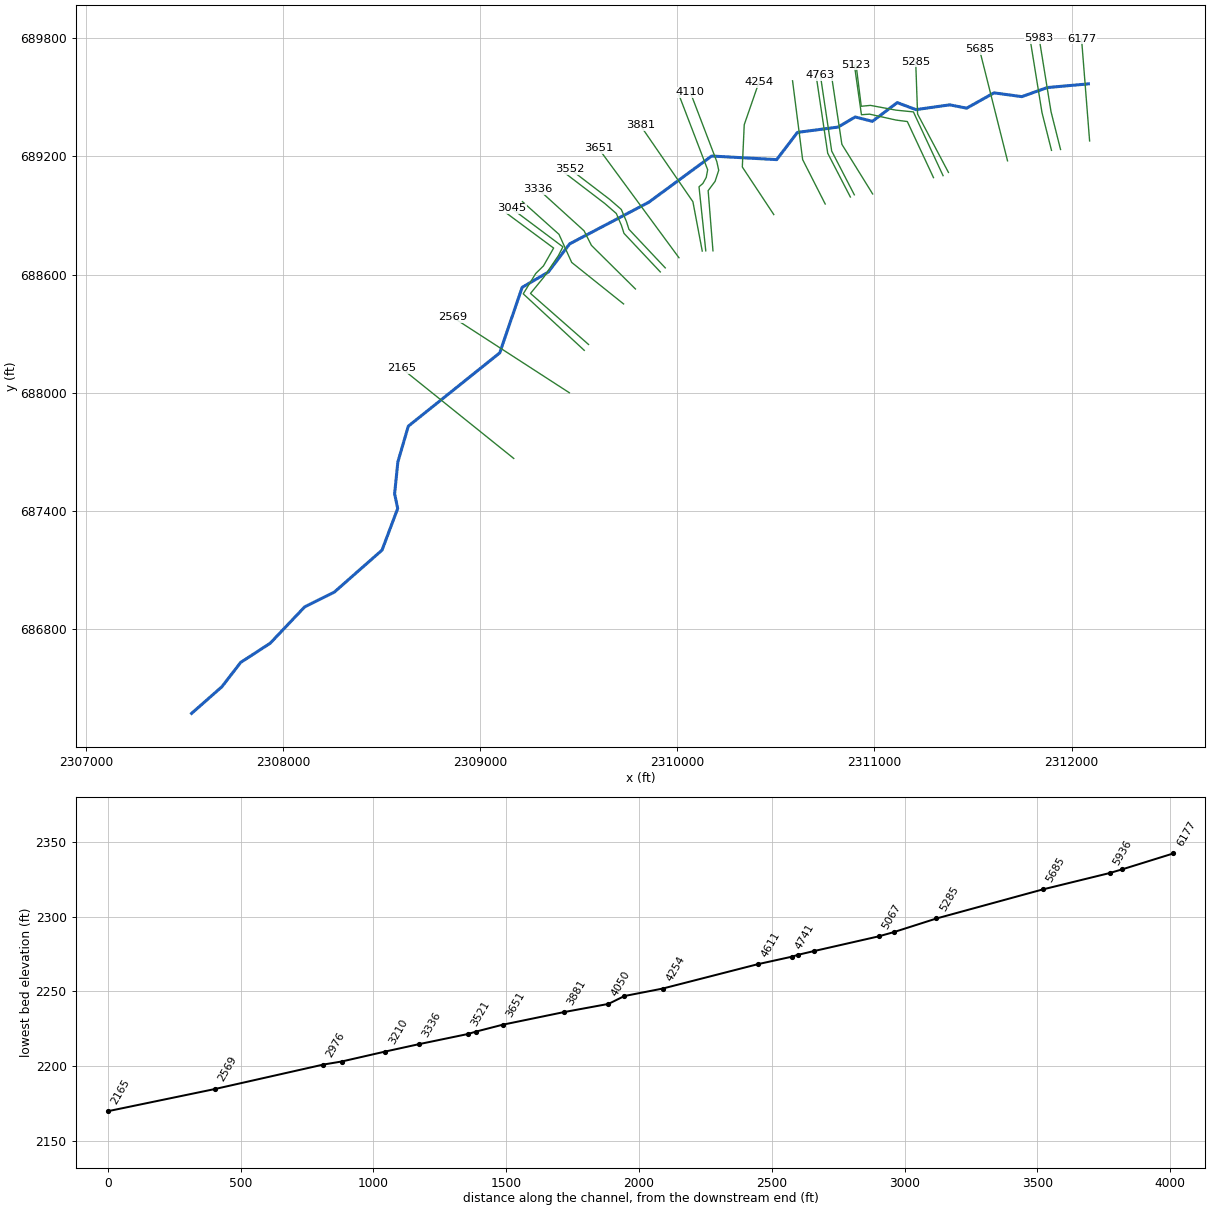
--- LAURELFK2.prj (project) ---

Proj Title=LAURELFK2
Current Plan=p01
Default Exp/Contr=0,0
English Units
Geom File=g01
Flow File=f01
Plan File=p01
BEGIN DESCRIPTION:
----------MODEL BY WSP USA 2022----------
AFH study
Randolph County, WV
HEC-RAS Version: RAS 6.2
Vertical Datum: NAVD88
Projection: NAD 1983 StatePlane West Virginia S FIPS 4702 (US Feet)
Terrain: 1-meter LIDAR (FEMA Region III 3DEP collected 2016-2018)
Land Use: 2019 NLCD
Hydrologic Method:
WV SIR2010-5033 regression equations
Additional Model Notes:
None
END DESCRIPTION:
DSS Export Rating Curves= 0
DSS Export Rating Curve Sorted= 0
DSS Export Volume Flow Curves= 0
DXF OffsetX= 0
DXF OffsetY= 0
DXF ScaleX= 0
DXF ScaleY= 0

--- LAURELFK2.p01 (plan) ---

Plan Title=Floodplain
Program Version=6.20
Short Identifier=Floodplain
Geom File=g01
Flow File=f01
Subcritical Flow
K Sum by GR= 0
Std Step Tol= 0.01
Critical Tol= 0.01
Num of Std Step Trials= 20
Max Error Tol= 0.3
Flow Tol Ratio= 0.001
Split Flow NTrial= 30
Split Flow Tol= 0.02
Split Flow Ratio= 0.02
Log Output Level= 0
Friction Slope Method= 1
Unsteady Friction Slope Method= 2
Unsteady Bridges Friction Slope Method= 1
Parabolic Critical Depth
Global Vel Dist= 0 , 0 , 0
Global Log Level= 0
CheckData=True
Encroach Param=-1 ,0,0, 0
Computation Interval=1MIN
Output Interval=1HOUR
Instantaneous Interval=1HOUR
Mapping Interval=1HOUR
Computation Time Step Use Courant=        0
Computation Time Step Use Time Series=    0
Computation Time Step Count To Double=0
Computation Time Step Max Doubling=0
Computation Time Step Max Halving=0
Computation Time Step Residence Courant=0
Run HTab= 0
Run UNet= 0
Run Sediment= 0
Run PostProcess= 0
Run WQNet= 0
Run RASMapper=-1
UNET Theta= 1
UNET Theta Warmup= 1
UNET ZTol= 0.02
UNET ZSATol= 0.02
UNET MxIter= 20
UNET Max Iter WO Improvement= 0
UNET MaxInSteps= 0
UNET DtIC= 0
UNET DtMin= 0
UNET MaxCRTS= 20
UNET WFStab= 2
UNET SFStab= 1
UNET WFX= 1
UNET SFX= 1
UNET Gravity=32.174
UNET 1D Methodology=Finite Difference
UNET DSS MLevel= 4
UNET Pardiso=0
UNET DZMax Abort= 100
UNET Use Existing IB Tables=-1
UNET Froude Reduction=False
UNET Froude Limit= 0.8
UNET Froude Power= 4
UNET D1 Cores= 0
UNET WindReference=Eulerian
UNET WindDragFormulation=Hsu (1988)
UNET D2 Coriolis=0
UNET D2 Cores= 0
UNET D2 Theta= 1
UNET D2 Theta Warmup= 1
UNET D2 Z Tol= 0.01
UNET D2 Volume Tol= 0.01
UNET D2 Max Iterations= 20
UNET D2 Equation= 0
UNET D2 RampUpFraction=0.1
UNET D2 TimeSlices= 1
UNET D2 Turbulence Formulation=None
UNET D2 Eddy Viscosity=0.3
UNET D2 Transverse Eddy Viscosity=0.1
UNET D2 Smagorinsky Mixing=0.05
UNET D2 BCVolumeCheck=0
UNET D2 Cores=0
UNET D2 SolverType=PARDISO (Direct)
UNET D2 Minimum Iterations= 2147483647
UNET D2 Maximum Iterations= 2147483647
UNET D2 Restart Number= 10
UNET D2 Relaxation Coeff=1.3
UNET D2 SOR Precondition Iterations= 10
UNET D2 ILUT Maximum Fill= 8
UNET D2 ILUT Tolerance=1E-08
UNET D1D2 MaxIter= 0
UNET D1D2 ZTol=0.01
UNET D1D2 QTol=0.1
UNET D1D2 MinQTol=1
Write IC File= 0
Write IC File at Fixed DateTime=0
Write IC File at Sim End=0
Echo Input=False
Echo Parameters=False
Echo Output=False
Write Detailed= 0
HDF Write Warmup=0
HDF Write Time Slices=0
HDF Flush=0
HDF Compression= 1
HDF Chunk Size= 1
HDF Spatial Parts= 1
HDF Use Max Rows=0
HDF Fixed Rows= 1
Calibration Method= 0
Calibration Iterations= 20
Calibration Max Change=0.05
Calibration Tolerance=0.2
Calibration Maximum=1.5
Calibration Minimum=0.5
Calibration Optimization Method= 1
WQ AD Non Conservative
WQ ULTIMATE=-1
WQ Max Comp Step=1HOUR
WQ Output Interval=15MIN
WQ Output Selected Increments= 0
WQ Output face flow=0
WQ Output face velocity=0
WQ Output face area=0
WQ Output face dispersion=0
WQ Output cell volume=0
WQ Output cell surface area=0
WQ Output cell continuity=0
WQ Output cumulative cell continuity=0
WQ Output face conc=0
WQ Output face dconc_dx=0
WQ Output face courant=0
WQ Output face peclet=0
WQ Output face adv mass=0
WQ Output face disp mass=0
WQ Output cell mass=0
WQ Output cell source sink temp=0
WQ Output nsm pathways=0
WQ Output nsm derived pathways=0
WQ Create Restart=0
WQ Fixed Restart=0
WQ System Summary=0
WQ Write To DSS=0
Sorting and Armoring Iterations= 10
XS Update Threshold= 0.02
Bed Roughness Predictor= 0
Hydraulics Update Threshold= 0.02
Energy Slope Method= 1
Volume Change Method= 1
Sediment Retention Method= 0
Sediment TS Multiplier= 1
Warm Up Method= 0
XS Weighting Method= 0
Number of US Weighted Cross Sections= 1
Number of DS Weighted Cross Sections= 1
Upstream XS Weight=0
Main XS Weight=1
Downstream XS Weight=0
Number of DS XS's Weighted with US Boundary= 1
Upstream Boundary Weight= 1
Weight of XSs Associated with US Boundary= 0
Number of US XS's Weighted with DS Boundary= 1
Downstream Boundary Weight= 0.5
Weight of XSs Associated with DS Boundary= 0.5
Percentile Method= 0
Sediment Output Level= 3
Mass or Volume Output= 0
Output Increment Type= 1
Profile and TS Output Increment= 1
Transport Output Increment 1
XS Output Flag= 0
XS Output Increment= 10
Read HDF5 Sediment Hotstart= 0
Sediment Hotstart Type= 0
Write Gradation File= 0
Read Gradation Hotstart= 0
Write HDF5 File= 1
Write Binary Output= 1
Write DSS Sediment File= 0
DSS Sediment Output Type= 1
SV Curve= 0
Specific Gage Flag= 0
Subcell Erosion Methods= 0
Subcell Deposition Methods= 0
Advection Scheme= 1
Matrix Solver= 0
Implicit Weighting Factor= 1
Maximum Outer Loop Convergence Iterations= 5
Convergence Maximum Absolute= 0.001
Convergence RMSE= 0.0001
Grain Fractions Max Abs Error= 0.001
Max Subgrid Regions= 1
Max Subgrid Length Scale= 3.402823E+38
Initial Layer Thickness= 3.402823E+38
Min Layer Thickness= 3.402823E+38
Max Layer Thickness= 3.402823E+38
Number of Layers= 5

--- LAURELFK2.f01 (steady flow) ---

Flow Title=Flow
Program Version=6.20
Number of Profiles= 1
Profile Names=P100yr
River Rch & RM=LAURELFK2,Main,6177
     399
River Rch & RM=LAURELFK2,Main,3336
     445
Boundary for River Rch & Prof#=LAURELFK2,Main            , 1
Up Type= 0
Dn Type= 3
Dn Slope=0.03029
DSS Import GetInterval= 0
DSS Import GetPeak= 0
DSS Import FillOption= 0

--- LAURELFK2.g01 (geometry) ---

Geom Title=Geometry
Program Version=6.20

River Reach=LAURELFK2       ,Main
Reach XY= 30
2312085.40000004689568.4150000072311876.63200003689549.752000019
2311747.72600004 689503.745000022311606.66700003689522.841999993
2311467.77800001689445.1510000082311381.84100005689462.077999994
2311210.40000001689437.7730000172311115.34800003 689473.36300002
2310989.48000002689378.3110000042310902.24000002 689400.44600001
     2310815.001689349.2310000212310609.09400001689322.239000008
2310503.78200004689184.1120000182310173.72400004689202.313000008
2309854.28000002688967.5039999932309453.02099998688756.566000015
2309344.51400001688613.1200000052309212.13700002688535.967999995
     2309098.421688203.3980000022308634.44499999687831.436000019
2308581.49400005687650.012999997     2308565.001 687488.55400002
2308580.62600003687413.9009999932308501.19900003687202.530000001
2308259.01100004686989.4220000062308108.83700003686914.768999994
2307933.49000001686729.8740000132307783.75000003686632.650999993
2307688.69900003686509.387999997 2307534.8507048686374.171938624

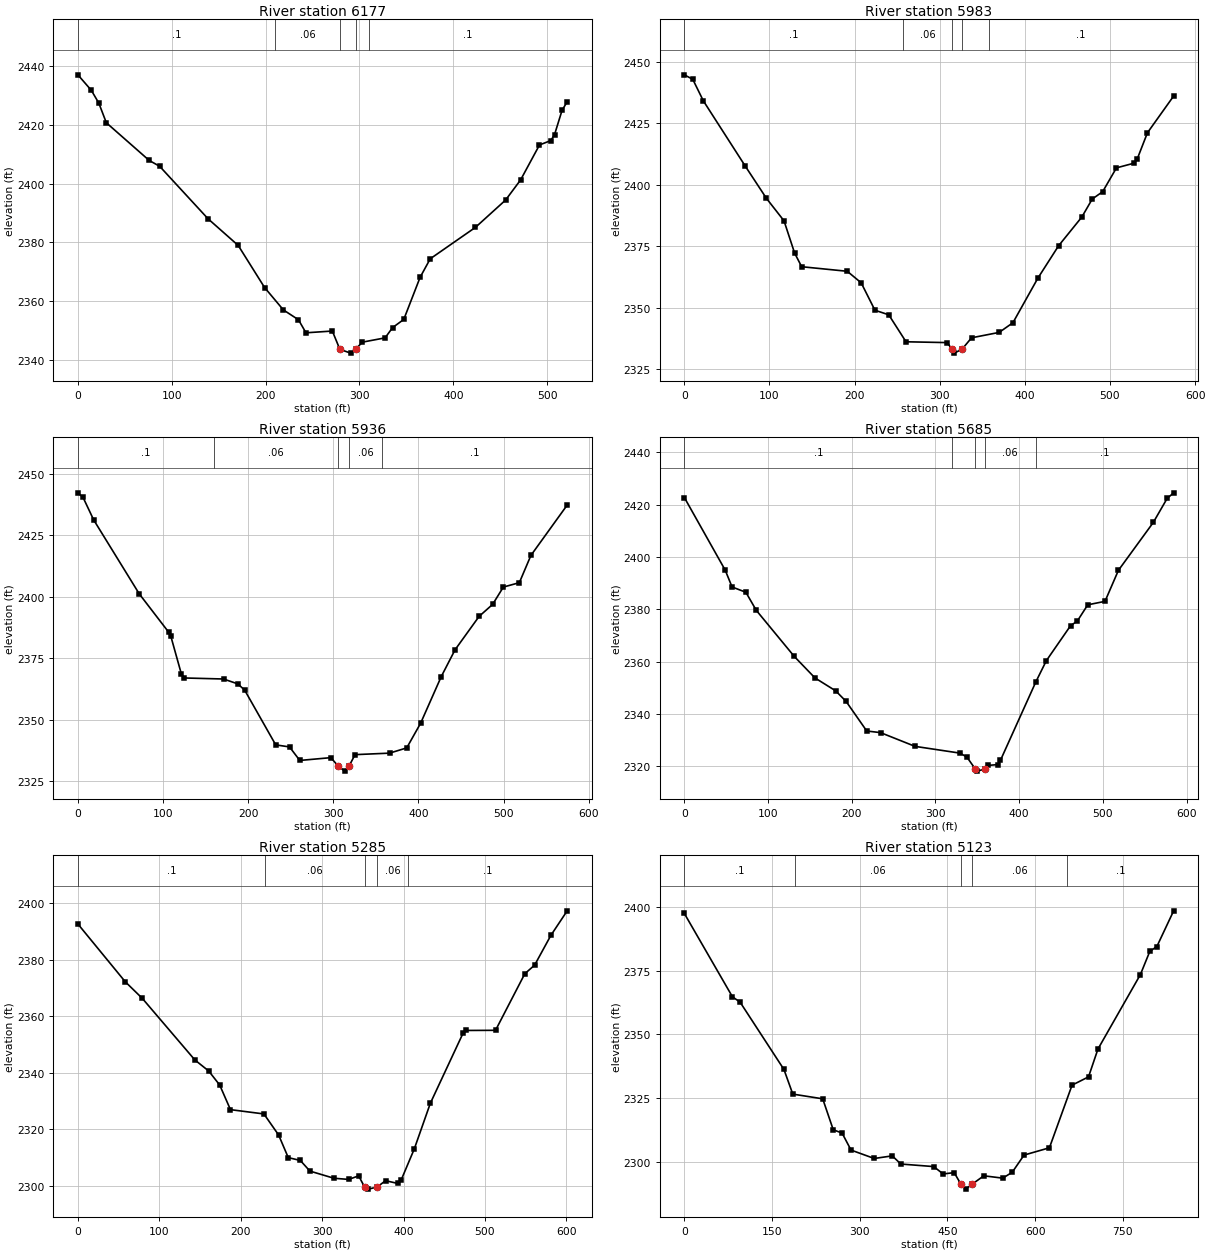
Type RM Length L Ch R = 1 ,6177    ,193.1,193.8,194.2
XS GIS Cut Line= 2
2312091.63675053689278.9317526822312050.59430663689798.661436405
#Sta/Elev= 30
       0 2437.05    14.3 2431.78    22.3 2427.41    30.3 2420.72      76 2407.86
    87.1 2405.88   138.7 2387.97   170.8 2378.89   198.9 2364.55   218.9 2356.92
     235 2353.56     243 2349.11   271.1 2349.71   279.1 2343.48   290.6 2342.18
  296.022343.604   303.2 2345.93   327.3 2347.38   335.3 2350.89   347.2 2353.66
   364.6 2368.02   375.4 2374.34   423.6 2385.06   455.7 2394.37   471.7 2401.24
   491.8 2413.15   503.8 2414.63   507.8 2416.63   515.8 2424.92   521.3 2427.88
#Mann= 5 ,-1,0
       0      .1       0     210     .06       0   279.1    .045       0
  296.02     .06       0     310      .1       0
Bank Sta=279.1,296.02
XS Rating Curve= 0 ,0
Exp/Cntr=0.3,0.1

Type RM Length L Ch R = 1 ,5983    ,46.4,46.7,46.3
XS GIS Cut Line= 3
2311944.13478486689235.5769375852311895.93910372689427.012931852
2311835.64150231689799.552511265
#Sta/Elev= 30
       0 2444.76     9.9 2442.93    22.3 2434.18    71.8 2407.48    96.5 2394.45
   117.1 2385.33   129.5 2372.24   137.8 2366.66   191.4  2364.8   207.7 2360.12
   223.9 2348.94   240.1  2347.1   260.4 2336.11     309 2335.77   314.2 2333.07
   317.1 2331.49  326.272333.106   337.4 2337.73   369.8 2339.92     386 2343.86
   415.3 2362.01   439.7 2375.21     467 2386.91   479.2 2394.22   491.4 2397.19
   507.6 2406.89   527.8 2408.76   531.9  2410.4     544 2421.17   574.8 2436.13
#Mann= 5 ,-1,0
       0      .1       0  257.41     .06       0   314.2    .045       0
  326.27     .06       0  357.41      .1       0
Bank Sta=314.2,326.27
XS Rating Curve= 0 ,0
Exp/Cntr(USF)=0,0
Exp/Cntr=0.3,0.1

Type RM Length L Ch R = 1 ,5936    ,251.4,251.4,252
XS GIS Cut Line= 3
2311898.23308497689231.2377610212311850.03740384689422.673755289
2311789.73980243689795.213334702
#Sta/Elev= 30
       0 2442.16     6.1 2440.28    18.5 2431.19    72.1 2401.09   106.7  2385.5
   109.2 2383.86   121.6  2368.5   125.2 2366.91   171.1 2366.49   187.8 2364.52
   195.9 2361.99   232.4 2339.72   248.6 2338.89   260.7 2333.39   297.2 2334.53
   305.8  2331.1   313.4 2329.05  318.562331.098   325.6 2335.75   366.1 2336.36
   386.3 2338.49   402.6  2348.5   426.9  2367.5   443.1 2378.38   471.4 2391.97
   487.2 2396.81   499.8 2403.86   518.6 2405.64   532.2 2416.73   574.8 2437.18
#Mann= 5 ,-1,0
       0      .1       0     160     .06       0   305.8    .045       0
  318.56     .06       0  357.41      .1       0
Bank Sta=305.8,318.56
XS Rating Curve= 0 ,0
Exp/Cntr(USF)=0,0
Exp/Cntr=0.3,0.1

Type RM Length L Ch R = 1 ,5685    ,400.7,400.2,397.7
BEGIN DESCRIPTION:
Structure XS 4
END DESCRIPTION:
XS GIS Cut Line= 2
2311675.14731912689177.8643528692311532.51362586689744.741851707
#Sta/Elev= 30
       0 2422.68    48.8 2394.93      57  2388.5    73.5 2386.47    85.9 2379.58
   131.3 2361.96     156 2353.75   180.8  2348.8   193.2 2344.78   217.9 2333.46
   234.4 2332.84   275.6 2327.59   329.3 2325.01   337.5  2323.5  347.66  2318.9
   349.9 2318.13   358.7 2318.89   362.3 2320.31   374.3 2320.62   377.6 2322.25
     420 2352.31   432.4 2360.32   461.3 2373.67   469.5 2375.51   481.9 2381.68
   502.5    2383   518.5 2394.85   560.2 2413.16   576.7 2422.32   584.5 2424.47
#Mann= 5 ,-1,0
       0      .1       0     320     .06       0  347.66    .045       0
   358.7     .06       0     420      .1       0
Bank Sta=347.66,358.7
XS Rating Curve= 0 ,0
Exp/Cntr(USF)=0,0
Exp/Cntr=0.3,0.1

Type RM Length L Ch R = 1 ,5285    ,153.1,161.8,176.2
XS GIS Cut Line= 3
2311375.33976733689119.1413514522311218.70907764689415.469683295
 2311209.1842384689681.106866483
#Sta/Elev= 30
       0 2392.64    58.1 2372.21    79.2 2366.27   143.7 2344.48   160.7 2340.57
   174.2  2335.6   187.4 2326.88   228.5 2325.36   246.6 2317.89   258.4 2309.89
   273.2 2308.89     285 2305.12   314.5 2302.58   332.6 2302.17   344.9 2303.43
  352.11 2299.48   356.9 2298.73   367.72299.503   377.9 2301.72   392.9 2300.75
   396.9 2301.82   413.2 2312.97   432.9 2329.13     473  2353.9     477 2354.93
     513 2354.98     549 2375.04     561 2378.06     581 2388.62     601  2397.3
#Mann= 5 ,-1,0
       0      .1       0     230     .06       0  352.11    .045       0
   367.7     .06       0  405.18      .1       0
Bank Sta=352.11,367.7
XS Rating Curve= 0 ,0
Exp/Cntr(USF)=0,0
Exp/Cntr=0.3,0.1

Type RM Length L Ch R = 1 ,5123    ,53.9,55.5,53.3
BEGIN DESCRIPTION:
Structure XS 3
END DESCRIPTION:
XS GIS Cut Line= 6
2311348.05024211689102.6387656462311197.54513157689426.224753301
2311108.74711636689435.2550599332310979.31272129689459.335877619
2310932.93997137689454.8477561462310906.60594308689665.622490506
#Sta/Elev= 30
       0 2397.31    82.2 2364.76    95.4 2362.63   170.4 2336.32   185.5  2326.7
   236.7 2324.86   254.7 2312.76   269.8 2311.48   285.1 2304.83   324.8 2301.54
   355.7 2302.56   370.3 2299.37   426.6 2298.37   442.7 2295.49   461.6 2296.01
   473.12291.483   481.5 2289.56   492.7 2291.56   512.3 2294.77   544.7 2293.85
   560.9 2296.16   581.1 2302.87   624.5 2305.72   663.2  2330.2   691.4 2333.44
   707.5 2344.31   780.1 2373.42   796.2 2382.48   808.3 2384.39     837 2398.34
#Mann= 5 ,-1,0
       0      .1       0     190     .06       0   473.1    .045       0
   492.7     .06       0  654.54      .1       0
Bank Sta=473.1,492.7
XS Rating Curve= 0 ,0
Exp/Cntr(USF)=0,0
Exp/Cntr=0.3,0.1

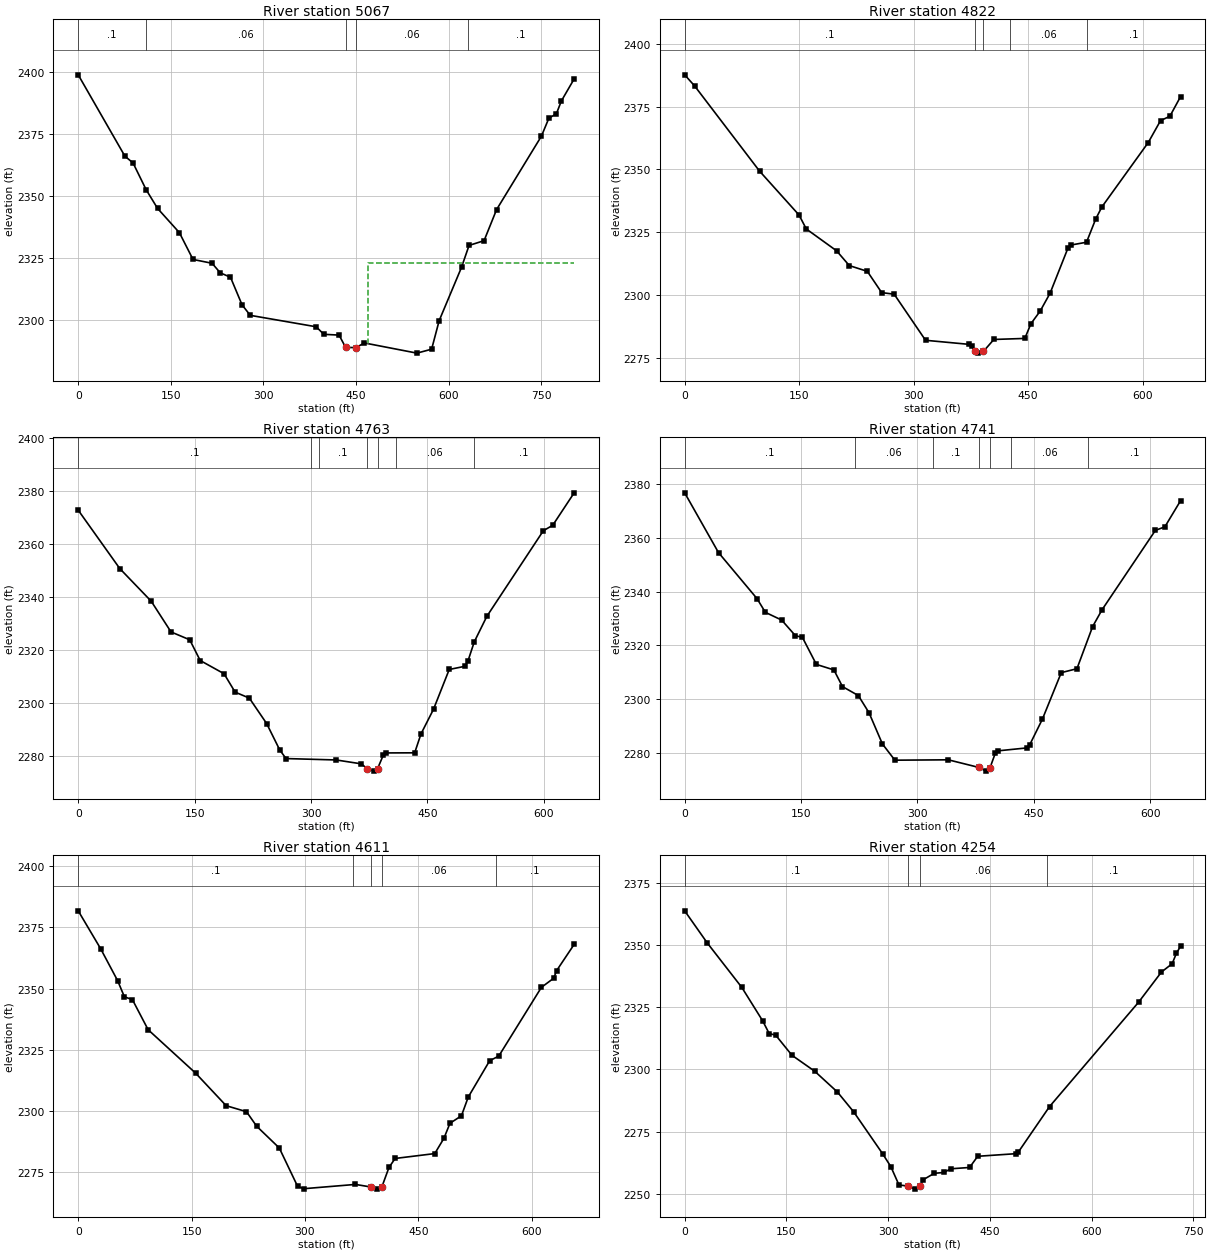
Type RM Length L Ch R = 1 ,5067    ,255,245.5,237.5
BEGIN DESCRIPTION:
Structure XS 2 Disconnected without IFA
END DESCRIPTION:
XS GIS Cut Line= 6
2311299.42956615689092.7055788562311166.69158391689377.310592376
2311109.49964191689384.8358479032310975.12792669689414.841449771
2310933.84198086689411.8469813362310898.45547385689661.663915871
#Sta/Elev= 30
       0 2398.69    75.6 2365.99    88.8 2363.26     110 2352.51   128.5 2344.99
   163.8 2335.25   185.9 2324.47   216.8 2322.93     230 2319.09   246.6 2317.31
   265.3 2306.23   278.6    2302   385.4  2297.4   397.7 2294.37   422.4 2294.06
   433.1 2289.08   449.9 2289.05   463.4  2290.9   548.5 2286.81   572.3 2288.39
   584.5 2299.86   620.7  2321.3   632.9 2330.11   657.2 2332.01   677.5 2344.52
   750.1 2374.04   762.2 2381.28   774.3 2383.01   782.4 2388.19   803.1 2397.05
#Mann= 5 ,-1,0
       0      .1       0     110     .06       0   433.1    .045       0
   449.9     .06       0   630.8      .1       0
#XS Ineff= 2 , 0
                          469.55         2322.98
Permanent Ineff=
       F       F
Bank Sta=433.1,449.9
XS Rating Curve= 0 ,0
Exp/Cntr(USF)=0,0
Exp/Cntr=0.3,0.1

Type RM Length L Ch R = 1 ,4822    ,58.3,58.8,59.1
XS GIS Cut Line= 3
 2310990.7915304689009.799175189 2310834.5603548689261.852138488
2310781.78893549689611.115611047
#Sta/Elev= 30
       0 2387.66    13.1 2383.21    98.1 2349.34   149.9 2331.84   159.3 2326.33
     199 2317.63   215.7 2311.74   239.3 2309.45   258.1 2300.99   274.5 2300.35
   315.6 2282.01   372.7 2280.39   376.8 2279.72   380.8 2277.61   384.9  2276.9
  391.38 2277.58   405.1 2282.34   445.7 2282.75   453.6 2288.58   465.8 2293.64
   478.8 2300.77   502.2 2318.72   506.2 2319.93   526.5 2321.03   538.6 2330.32
   546.7 2335.11   607.4 2360.72   623.5 2369.44   635.7 2371.16   649.8 2379.03
#Mann= 5 ,-1,0
       0      .1       0   380.8    .045       0  391.38      .1       0
  426.54     .06       0  526.54      .1       0
Bank Sta=380.8,391.38
XS Rating Curve= 0 ,0
Exp/Cntr(USF)=0,0
Exp/Cntr=0.3,0.1

Type RM Length L Ch R = 1 ,4763    ,21.7,21.8,21.7
XS GIS Cut Line= 3
2310897.74644365689005.5643924422310782.87688244689227.588395075
2310725.44210184689612.487148675
#Sta/Elev= 30
       0 2372.66    53.6 2350.68    94.1 2338.39   119.6 2326.84   143.7 2323.89
   157.2 2316.09   187.9 2311.12   202.2 2304.19   220.5 2301.94   242.8 2292.38
   259.7 2282.43   267.8 2279.19   332.5 2278.66   364.8  2277.2   372.3 2275.42
     381 2274.46  385.78  2275.4   393.1 2280.45   397.2 2281.31   433.6 2281.35
   441.7 2288.45   457.9 2297.77   478.1 2312.71   498.3 2313.91   502.3 2315.95
   510.4 2323.12   526.6 2332.71   599.4 2364.93   611.5 2366.98   639.1 2379.19
#Mann= 7 ,-1,0
       0      .1       0  299.98     .06       0  309.98      .1       0
   372.3    .045       0  385.78      .1       0  409.98     .06       0
  509.98      .1       0
Bank Sta=372.3,385.78
XS Rating Curve= 0 ,0
Exp/Cntr(USF)=0,0
Exp/Cntr=0.3,0.1

Type RM Length L Ch R = 1 ,4741    ,130,130,129.7
XS GIS Cut Line= 3
2310877.60140866688994.4203305342310762.73184745689216.444333167
2310705.29706685689601.343086767
#Sta/Elev= 30
       0 2376.79    43.6 2354.55    93.2 2337.44     104 2332.33     125 2329.45
   142.7 2323.64   151.7 2323.02   169.7 2312.96   192.3 2310.91   203.3 2304.72
   223.8 2301.37   237.6 2294.95   254.8 2283.37   270.9 2277.33   339.7 2277.47
  379.43 2274.61   388.2 2273.26   393.6  2274.6   400.4 2280.03   404.2 2280.82
   440.8 2281.89   444.8 2283.16     461 2292.61   485.3  2309.9   505.5 2311.36
   525.7 2327.03   537.8 2333.27   606.6 2362.83   618.8 2364.14   639.1 2373.89
#Mann= 7 ,-1,0
       0      .1       0     220     .06       0  319.98      .1       0
  379.43    .045       0   393.6      .1       0  419.98     .06       0
  519.98      .1       0
Bank Sta=379.43,393.6
XS Rating Curve= 0 ,0
Exp/Cntr(USF)=0,0
Exp/Cntr=0.3,0.1

Type RM Length L Ch R = 1 ,4611    ,358.1,357.6,354.1
BEGIN DESCRIPTION:
Structure XS 1
END DESCRIPTION:
XS GIS Cut Line= 3
2310750.07339844688958.7115342342310635.47880728689184.243442374
2310584.27696868689584.105420049
#Sta/Elev= 30
       0 2381.78    29.7  2366.3    52.1  2353.3    61.1 2346.68    71.7 2345.53
    92.5 2333.25   155.3 2315.53   195.7 2302.24   222.6 2299.79   236.1 2293.85
     266 2284.98   290.2 2269.34   298.3 2268.35   366.8  2270.1     387 2269.06
   395.1 2268.18  401.66 2269.04   411.2 2277.09   419.3  2280.7   471.7 2282.69
   483.8 2288.92   491.8 2295.05     507 2298.13     516 2305.76   544.3 2320.58
   556.4  2322.5   612.8 2350.55     629 2354.26     633 2357.42   656.1 2368.08
#Mann= 5 ,-1,0
       0      .1       0  362.98     .06       0     387    .045       0
  401.66     .06       0  552.98      .1       0
Bank Sta=387,401.66
XS Rating Curve= 0 ,0
Exp/Cntr(USF)=0,0
Exp/Cntr=0.3,0.1

Type RM Length L Ch R = 1 ,4254    ,140,143.8,149.4
BEGIN DESCRIPTION:
Structure XS 4
END DESCRIPTION:
XS GIS Cut Line= 4
2310489.05827726688905.2824677352310329.35730447689146.662564014
2310339.11003563689361.2226495962310413.47461075689575.782735178
#Sta/Elev= 30
       0 2363.71    33.4 2350.77    84.3 2332.93     115 2319.52   124.6 2314.42
   134.2 2313.77   158.2 2305.69   191.7 2299.29   225.3 2290.91   249.3 2282.93
   291.9 2266.13     304 2260.96     316 2253.59     329 2253.18     340 2251.93
  346.382253.222     352 2255.75     368 2258.28   382.6 2258.63   392.1 2260.09
   420.1 2260.63   432.1 2265.12   488.1 2266.16   492.2  2266.9     538 2285.08
   669.3    2327   703.1 2339.15   718.8 2342.45   725.1 2346.66   731.3 2349.53
#Mann= 4 ,-1,0
       0      .1       0     329    .045       0  346.38     .06       0
  534.21      .1       0
Bank Sta=329,346.38
XS Rating Curve= 0 ,0
Exp/Cntr(USF)=0,0
Exp/Cntr=0.3,0.1

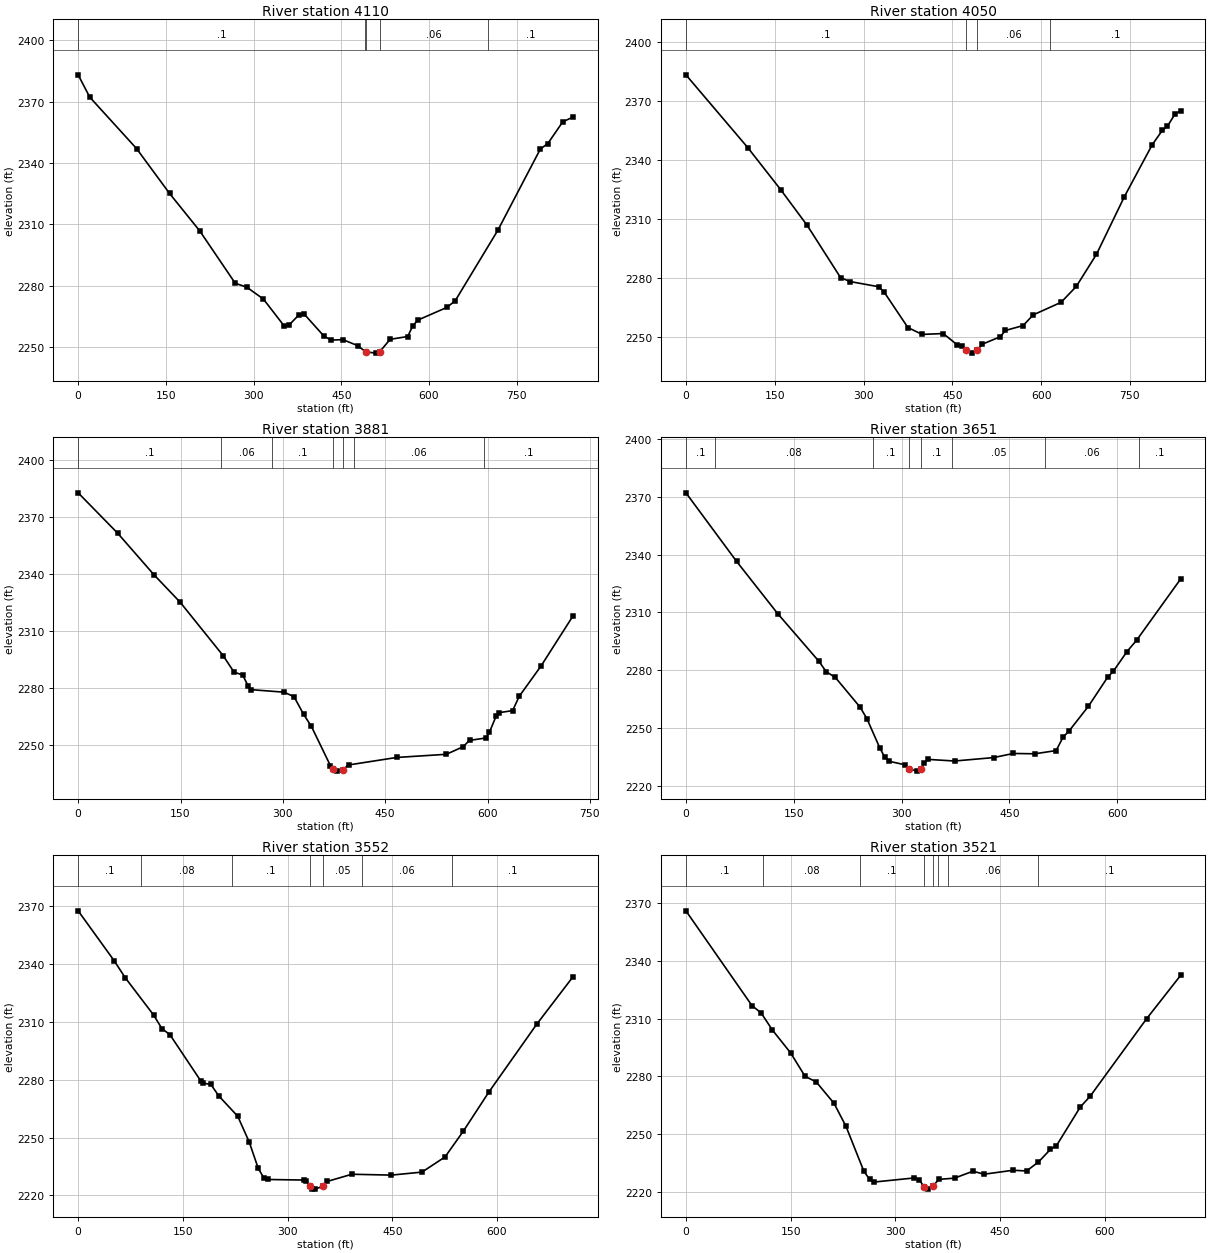
Type RM Length L Ch R = 1 ,4110    ,60,60.1,59.7
BEGIN DESCRIPTION:
Structure XS 3
END DESCRIPTION:
XS GIS Cut Line= 6
2310180.46169558688721.4093206562310156.00461512689026.573482781
2310191.35826559  689074.11804722310209.64463652689130.196251386
2310199.89190535689174.0835416182310065.79185187689525.181863479
#Sta/Elev= 30
       0 2383.16    19.8 2372.25    99.8 2347.09   156.3 2325.11   208.1 2306.72
   268.6 2281.17   288.7 2279.17   316.8 2273.43   352.3 2260.28   360.2 2260.55
     378 2265.83   386.4 2266.13   420.1 2255.36   432.5 2253.36     453 2253.54
   477.9 2250.65     492 2247.56   509.7 2246.96  515.522247.557   533.6 2253.72
   563.6 2255.08   572.1 2260.18   580.7 2263.09   630.5 2269.32   644.9 2272.59
   717.7 2307.05   790.5 2346.85   803.3 2349.55   828.8 2360.16   846.2 2362.47
#Mann= 5 ,-1,0
       0      .1       0  490.33     .06       0     492    .045       0
  515.52     .06       0  700.33      .1       0
Bank Sta=492,515.52
XS Rating Curve= 0 ,0
Exp/Cntr(USF)=0,0
Exp/Cntr=0.3,0.1

Type RM Length L Ch R = 1 ,4050    ,167,168.7,172
BEGIN DESCRIPTION:
Structure XS 2
END DESCRIPTION:
XS GIS Cut Line= 6
2310143.88895372688721.334068101 2310109.6791421689046.078945107
2310129.18460442689063.1462246422310146.25188396689093.623509525
2310153.56643233689132.6344341762310007.27546489689514.210040921
#Sta/Elev= 30
       0 2383.24   104.4 2346.26   160.7 2324.59     205 2306.61   261.3 2280.08
   277.4 2278.09   325.6 2275.46   335.2 2272.59     375  2254.7   399.1 2251.21
   434.7 2251.65   457.8 2246.03   466.4 2245.53  472.762243.311   483.7 2241.69
   492.3 2243.33   500.9 2246.25   531.1 2250.04   539.7 2253.21   569.6  2255.7
   586.7 2261.14   633.8 2267.54   659.4 2275.59   693.6 2291.98   740.6 2321.21
   787.6 2347.62   804.7 2354.95   813.3    2357   826.1 2363.25   835.8 2365.06
#Mann= 4 ,-1,0
       0      .1       0  472.76    .045       0   492.3     .06       0
  615.25      .1       0
Bank Sta=472.76,492.3
XS Rating Curve= 0 ,0
Exp/Cntr(USF)=0,0
Exp/Cntr=0.3,0.1

Type RM Length L Ch R = 1 ,3881    ,229.7,230,230.2
BEGIN DESCRIPTION:
Structure XS 1
END DESCRIPTION:
XS GIS Cut Line= 3
2310126.00643316688720.2126545222310078.62593576 688970.47818888
2309812.04151479689357.982620728
#Sta/Elev= 30
       0 2382.81      58  2361.5   110.9 2339.73   149.6 2325.13   212.7 2296.92
   228.3  2288.4   241.2 2286.78   249.3 2280.92   253.4  2279.1   301.6 2277.78
   316.3 2275.44   330.3 2266.18   341.8 2259.76   369.7 2239.05   373.5 2237.08
   379.4 2236.18   387.9 2237.03   396.5 2239.44   466.8 2243.38   539.6 2245.05
   563.9 2248.98   573.6 2252.37   597.8 2253.66   602.7 2256.67   612.4 2265.01
   617.3 2267.02   636.7 2268.05   646.4 2275.59   678.4 2291.59   725.1 2317.89
#Mann= 7 ,-1,0
       0      .1       0     210     .06       0  284.71      .1       0
   373.5    .045       0   387.9      .1       0  404.71     .06       0
  594.71      .1       0
Bank Sta=373.5,387.9
XS Rating Curve= 0 ,0
Exp/Cntr(USF)=0,0
Exp/Cntr=0.3,0.1

Type RM Length L Ch R = 1 ,3651    ,101.9,99.2,98
BEGIN DESCRIPTION:
Structure XS 4
END DESCRIPTION:
XS GIS Cut Line= 2
2310007.83885192 688686.242865252309599.91746103 689240.80266463
#Sta/Elev= 30
       0 2371.97    70.5 2336.45   127.7 2309.38     185 2284.71   195.2 2279.31
   207.9 2276.32   242.5 2260.85   251.9  2254.9   269.5 2240.02   276.8 2234.88
   282.2 2232.93   305.1 2231.04     3112228.998   321.4 2227.78  327.09 2229.01
   331.4 2232.15     337 2233.86   373.8 2233.02   428.2  2234.8   455.5 2236.93
   485.5 2236.76   515.1 2238.43     525 2245.53   532.7 2248.39     560 2261.37
   586.7 2276.38   594.6 2279.47   613.7 2289.71   627.2 2295.65   688.4 2327.35
#Mann= 8 ,-1,0
       0      .1       0      40     .08       0     260      .1       0
     311    .045       0  327.09      .1       0     370     .05       0
     500     .06       0     630      .1       0
Bank Sta=311,327.09
XS Rating Curve= 0 ,0
Exp/Cntr(USF)=0,0
Exp/Cntr=0.3,0.1

Type RM Length L Ch R = 1 ,3552    ,31.2,31.4,31.7
BEGIN DESCRIPTION:
Structure XS 3
END DESCRIPTION:
XS GIS Cut Line= 6
2309938.37740701688634.7251129082309754.09291983688830.527380535
2309741.13541682688870.8396121052309715.22041081688931.307959461
2309656.19178601688982.4181102022309454.63062816689136.468423703
#Sta/Elev= 30
       0  2367.6    51.4 2341.82    67.4 2332.92   108.3 2313.45   119.9 2306.55
   131.6 2303.28   175.9 2279.25   178.7 2278.25   190.1 2277.53   201.6 2271.53
   228.6 2261.04   245.1 2247.66     258 2233.99   265.8 2229.21   271.7 2228.24
   322.9 2227.95   326.8 2227.33   332.1  2224.8   335.5 2223.45   339.8 2223.24
   350.4 2224.75   357.2 2227.27   392.1 2230.96   448.6 2230.51   492.6 2232.07
   525.6 2239.94   551.9 2253.35   588.3 2273.55   656.8 2308.72   708.8 2333.34
#Mann= 7 ,-1,0
       0      .1       0      90     .08       0     220      .1       0
   332.1    .045       0   350.4     .05       0  407.02     .06       0
   535.1      .1       0
Bank Sta=332.1,350.4
XS Rating Curve= 0 ,0
Exp/Cntr(USF)=0,0
Exp/Cntr=0.3,0.1

Type RM Length L Ch R = 1 ,3521    ,184.3,184.8,185.1
BEGIN DESCRIPTION:
Structure XS 2
END DESCRIPTION:
XS GIS Cut Line= 6
2309913.18226228688614.209066483 2309728.8977751688810.011334111
2309715.94027209688850.3235656812309690.02526608688910.791913037
2309630.99664128688961.9020637782309429.43548343689115.952377279
#Sta/Elev= 30
       0 2365.83    94.9 2316.58   107.5 2313.04     124    2304     150  2292.2
   170.7 2280.05   186.7 2277.15   212.2 2266.06   229.3 2254.16   254.7 2231.08
   263.1 2226.61   268.9 2225.23   327.3  2227.4   334.6 2226.46   340.7 2222.88
   346.8 2221.59   353.72222.988   362.1 2226.63   384.8 2227.28   411.2 2230.88
   427.1 2229.32   468.7 2231.37     488    2231   505.1 2235.65   522.2 2242.21
   530.8 2244.08     565 2264.15   579.1 2269.71     660 2309.91   708.8 2332.41
#Mann= 8 ,-1,0
       0      .1       0     110     .08       0     250      .1       0
   340.7    .045       0   353.7      .1       0  361.23     .05       0
  375.11     .06       0   505.1      .1       0
Bank Sta=340.7,353.7
XS Rating Curve= 0 ,0
Exp/Cntr(USF)=0,0
Exp/Cntr=0.3,0.1

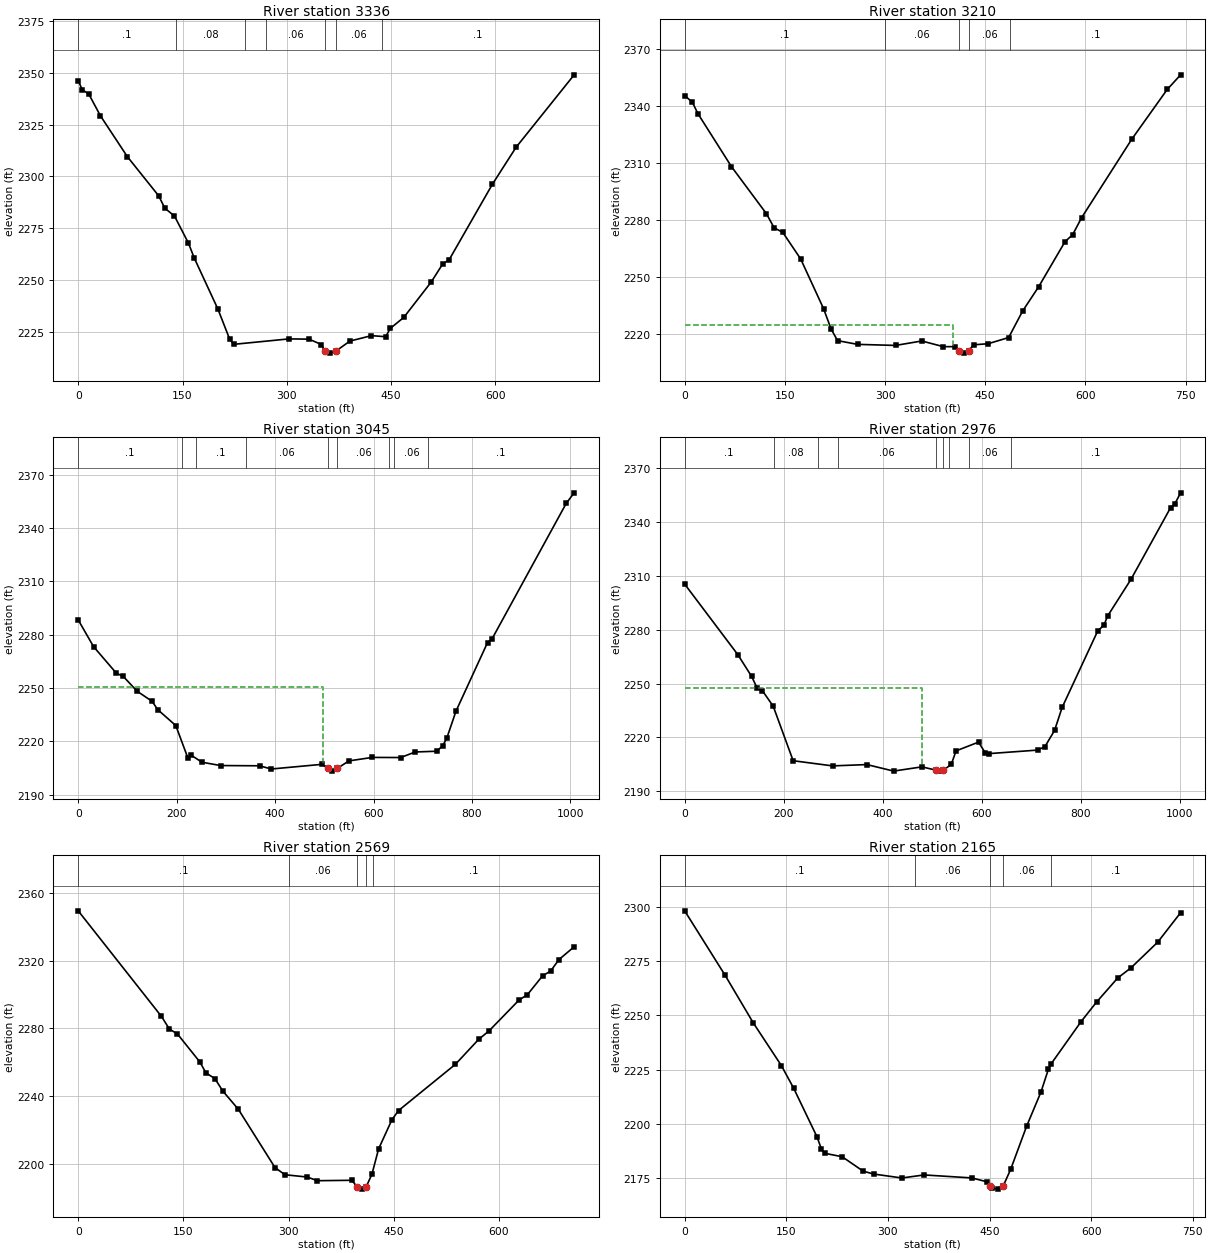
Type RM Length L Ch R = 1 ,3336    ,126.6,126.2,125.8
BEGIN DESCRIPTION:
Structure XS 1
END DESCRIPTION:
XS GIS Cut Line= 4
2309786.94657934688527.7979384842309563.78958316688748.795350843
2309526.35679669688822.9410624812309292.40188133689035.300139504
#Sta/Elev= 30
       0 2346.24     5.8 2341.84    15.2 2339.76      32 2329.24    70.8  2309.5
   115.7 2290.67   124.6 2284.67   138.4 2280.94   158.5 2267.85   166.8 2260.71
   200.9 2236.01   217.9 2221.41   223.6 2219.03   303.2 2221.66   331.9 2221.53
   349.8 2218.93   354.8 2215.75   361.7 2214.79   370.6  2215.8   390.7  2220.6
   421.7 2223.22   442.1 2222.71   448.7 2226.71   468.2 2232.04   507.6 2249.11
   524.3 2257.91   533.3 2259.79   595.6 2296.29   629.6 2314.09   713.1 2349.04
#Mann= 7 ,-1,0
       0      .1       0     140     .08       0     240      .1       0
     270     .06       0   354.8    .045       0   370.6     .06       0
  437.13      .1       0
Bank Sta=354.8,370.6
XS Rating Curve= 0 ,0
Exp/Cntr(USF)=0,0
Exp/Cntr=0.3,0.1

Type RM Length L Ch R = 1 ,3210    ,175.6,164.2,161.3
BEGIN DESCRIPTION:
Structure XS 4
END DESCRIPTION:
XS GIS Cut Line= 4
2309726.90096407688451.7546634592309463.51702063688662.461818211
2309399.12771308 688804.983126142309213.67853714688970.997294812
#Sta/Elev= 30
       0 2345.61    11.5 2342.09      20 2335.99    70.1 2308.14   122.5 2283.31
   133.9 2275.94   146.9 2273.52   173.7  2259.5   207.9 2233.37   219.2 2222.63
   228.9 2216.46   259.1 2214.49   315.7 2213.94   355.1 2216.28   387.2  2213.3
   405.4 2213.28   411.4 2211.05   417.5 2209.88  425.06 2211.09   432.6 2214.25
   454.4 2214.84   485.1 2218.09     506 2232.05   529.9 2244.78   569.6 2268.68
   580.9 2272.27   594.3 2281.23   669.4 2322.59   722.5 2348.83   742.6 2356.55
#Mann= 5 ,-1,0
       0      .1       0     300     .06       0   411.4    .045       0
  425.06     .06       0   487.3      .1       0
#XS Ineff= 2 , 0
          402.07 2224.45
Permanent Ineff=
       F       F
Bank Sta=411.4,425.06
XS Rating Curve= 0 ,0
Exp/Cntr(USF)=0,0
Exp/Cntr=0.3,0.1

Type RM Length L Ch R = 1 ,3045    ,63.5,69.2,69.4
BEGIN DESCRIPTION:
Structure XS 3
END DESCRIPTION:
XS GIS Cut Line= 6
2309549.06167758688246.107514204  2309254.523101688505.108357511
 2309322.9543583688588.6478144692309396.71792136688697.960082616
2309418.93586204688741.5072463492309157.65287964688937.025124335
#Sta/Elev= 30
       0 2288.28    31.1 2273.28    77.3 2258.37    91.7 2256.45   119.7 2248.16
   150.2 2242.48   161.5 2237.82   198.3 2228.84   222.7 2210.66   229.5 2212.18
   251.5 2208.24   289.1 2206.37   368.4 2206.23   392.2 2204.42   495.7 2207.06
   506.62204.805   514.7 2203.23   526.6 2204.82     550 2208.99   597.4 2210.94
   655.1 2210.87   684.6    2214   728.6 2214.42   740.7 2217.62   748.6 2221.63
   767.4 2236.94   831.5 2275.51   840.8 2277.66   991.5 2353.87  1007.5 2359.75
#Mann= 9 ,-1,0
       0      .1       0     210     .08       0     240      .1       0
     340     .06       0   506.6    .045       0   526.6     .06       0
  632.25      .1       0  642.25     .06       0  711.14      .1       0
#XS Ineff= 2 , 0
          497.06 2250.79
Permanent Ineff=
       F       F
Bank Sta=506.6,526.6
XS Rating Curve= 0 ,0
Exp/Cntr(USF)=0,0
Exp/Cntr=0.3,0.1

Type RM Length L Ch R = 1 ,2976    ,398.2,406.9,412.6
BEGIN DESCRIPTION:
Structure XS 2
END DESCRIPTION:
XS GIS Cut Line= 6
2309527.35941256688216.2751286682309217.71354555688503.043306571
2309281.18462982688606.4221670132309320.28820542688644.637024983
2309371.83382779688735.2862229592309131.88006845688913.029748401
#Sta/Elev= 30
       0 2305.48   107.3 2266.15   135.2 2254.01   146.1 2247.61     157 2246.01
   178.8  2237.4   219.1 2206.98   298.7  2204.1     368 2204.83     422  2201.2
   479.2 2203.56   508.3 2201.68   516.9 2201.18  522.692201.744   538.5 2204.94
   548.1 2212.47   593.5 2217.35   606.7 2211.56   614.8 2210.95   712.8 2212.91
   727.6 2214.82   747.1  2223.9   762.4  2236.7     834  2279.2   847.1 2282.77
   854.1 2287.62   901.6 2308.21   981.5 2348.15   990.2 2350.36  1001.7 2356.39
#Mann= 9 ,-1,0
       0      .1       0     180     .08       0     270      .1       0
     310     .06       0   508.3    .045       0  522.69     .06       0
   533.9      .1       0  574.17     .06       0  658.85      .1       0
#XS Ineff= 2 , 0
          479.13 2247.45
Permanent Ineff=
       F       F
Bank Sta=508.3,522.69
XS Rating Curve= 0 ,0
Exp/Cntr(USF)=0,0
Exp/Cntr=0.3,0.1

Type RM Length L Ch R = 1 ,2569    ,404.7,404.4,404.7
BEGIN DESCRIPTION:
Structure XS 1
END DESCRIPTION:
XS GIS Cut Line= 2
2309451.81218537688001.059924041 2308857.9949741688385.391145577
#Sta/Elev= 30
       0 2349.66   118.7 2287.16     130  2279.7   141.6 2276.71   173.4 2260.23
   182.1 2253.75   194.9 2250.33   206.3 2242.93   228.3 2232.21   280.7 2197.63
   294.9 2193.42   326.7 2192.05   341.1 2189.89   390.3 2190.13   397.8 2186.22
   404.6  2184.9   410.6 2186.21   418.9  2193.7   428.4 2208.73   447.4 2225.96
   456.8 2231.41     538 2258.81   571.3 2273.65   585.6 2278.45   628.5 2296.76
   640.7 2300.05   662.2 2311.14   673.7 2313.99   685.7 2320.82   707.3 2328.38
#Mann= 5 ,-1,0
       0      .1       0     300     .06       0   397.8    .045       0
   410.6     .06       0     420      .1       0
Bank Sta=397.8,410.6
XS Rating Curve= 0 ,0
Exp/Cntr(USF)=0,0
Exp/Cntr=0.3,0.1

Type RM Length L Ch R = 1 ,2165    ,373.6,375.8,377.5
BEGIN DESCRIPTION:
Structure XS 4
END DESCRIPTION:
XS GIS Cut Line= 2
2309169.50111519687667.8068831662308598.94439852688126.385178807
#Sta/Elev= 30
       0 2298.12    59.7 2268.44   101.5 2246.42   142.7 2226.91   160.8 2216.51
   195.4 2194.03   201.8 2188.48   206.5 2186.54   232.4 2184.94   263.4 2178.31
   278.8 2176.98   320.6 2175.16   353.4 2176.56   423.6 2175.19   445.8 2173.44
   451.12171.584   454.3 2170.41   461.9 2170.03   470.4 2171.67   481.1 2179.09
   504.6 2198.91   525.8 2214.68   536.8 2225.16   540.5 2227.52   585.2 2247.18
   607.9 2256.11   639.2 2267.23   658.6 2271.84   698.2  2283.7     732 2297.27
#Mann= 5 ,-1,0
       0      .1       0     340     .06       0   451.1    .045       0
   470.4     .06       0     540      .1       0
Bank Sta=451.1,470.4
XS Rating Curve= 0 ,0
Exp/Cntr(USF)=0,0
Exp/Cntr=0.3,0.1