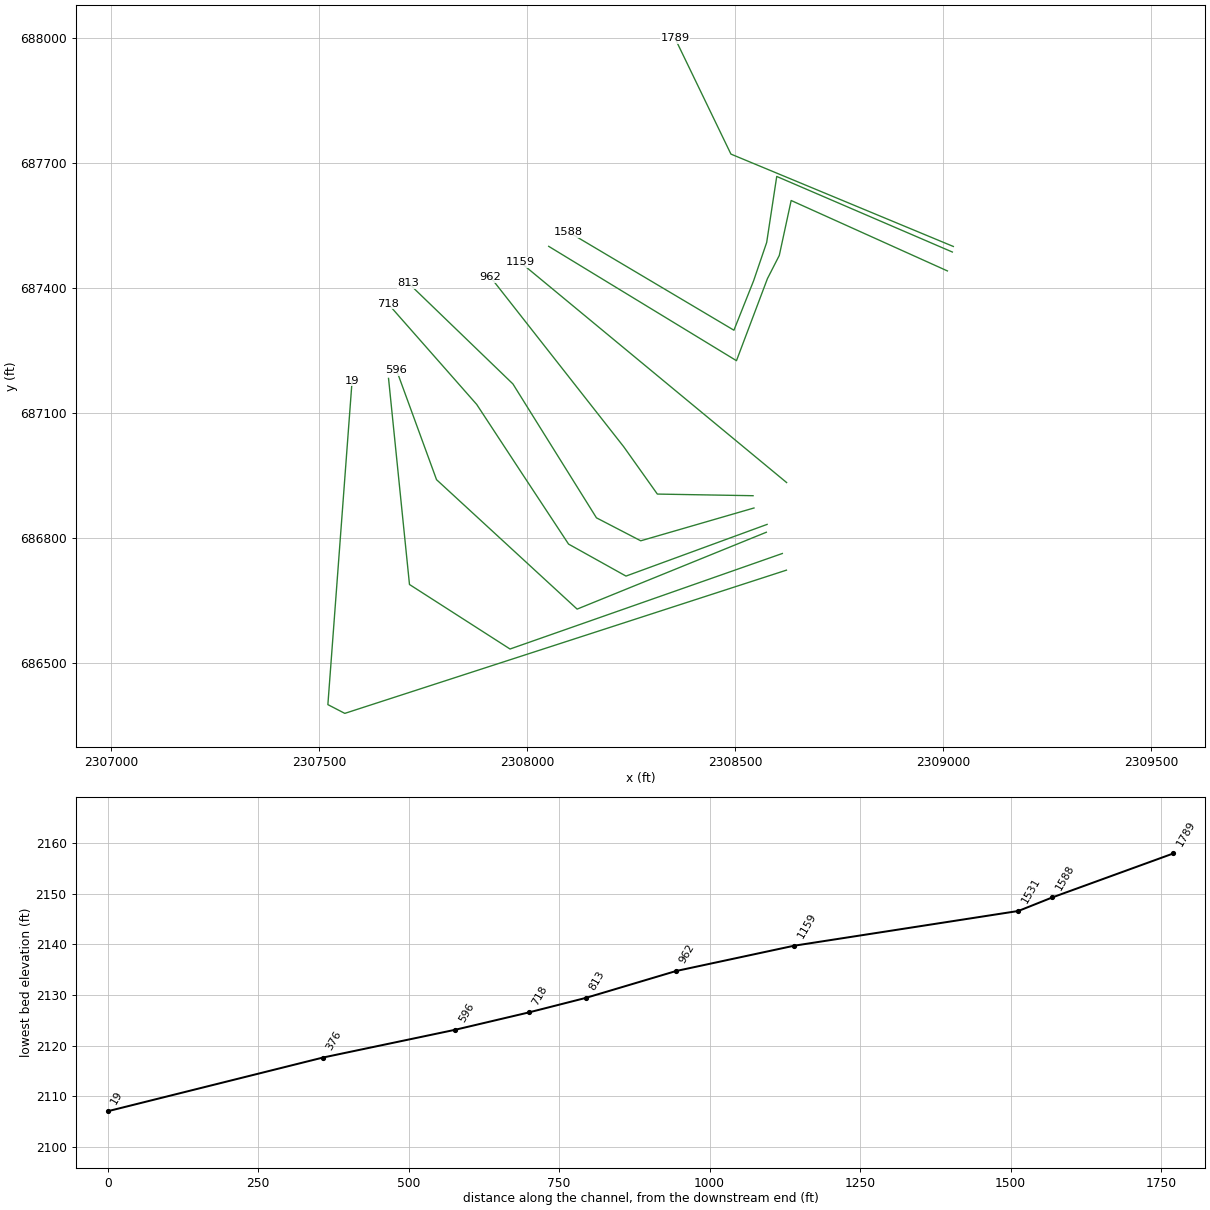
HEC-RAS study LAURELFK2.prj: LAURELFK2

--- LAURELFK2.g01 (geometry) --- (continued)

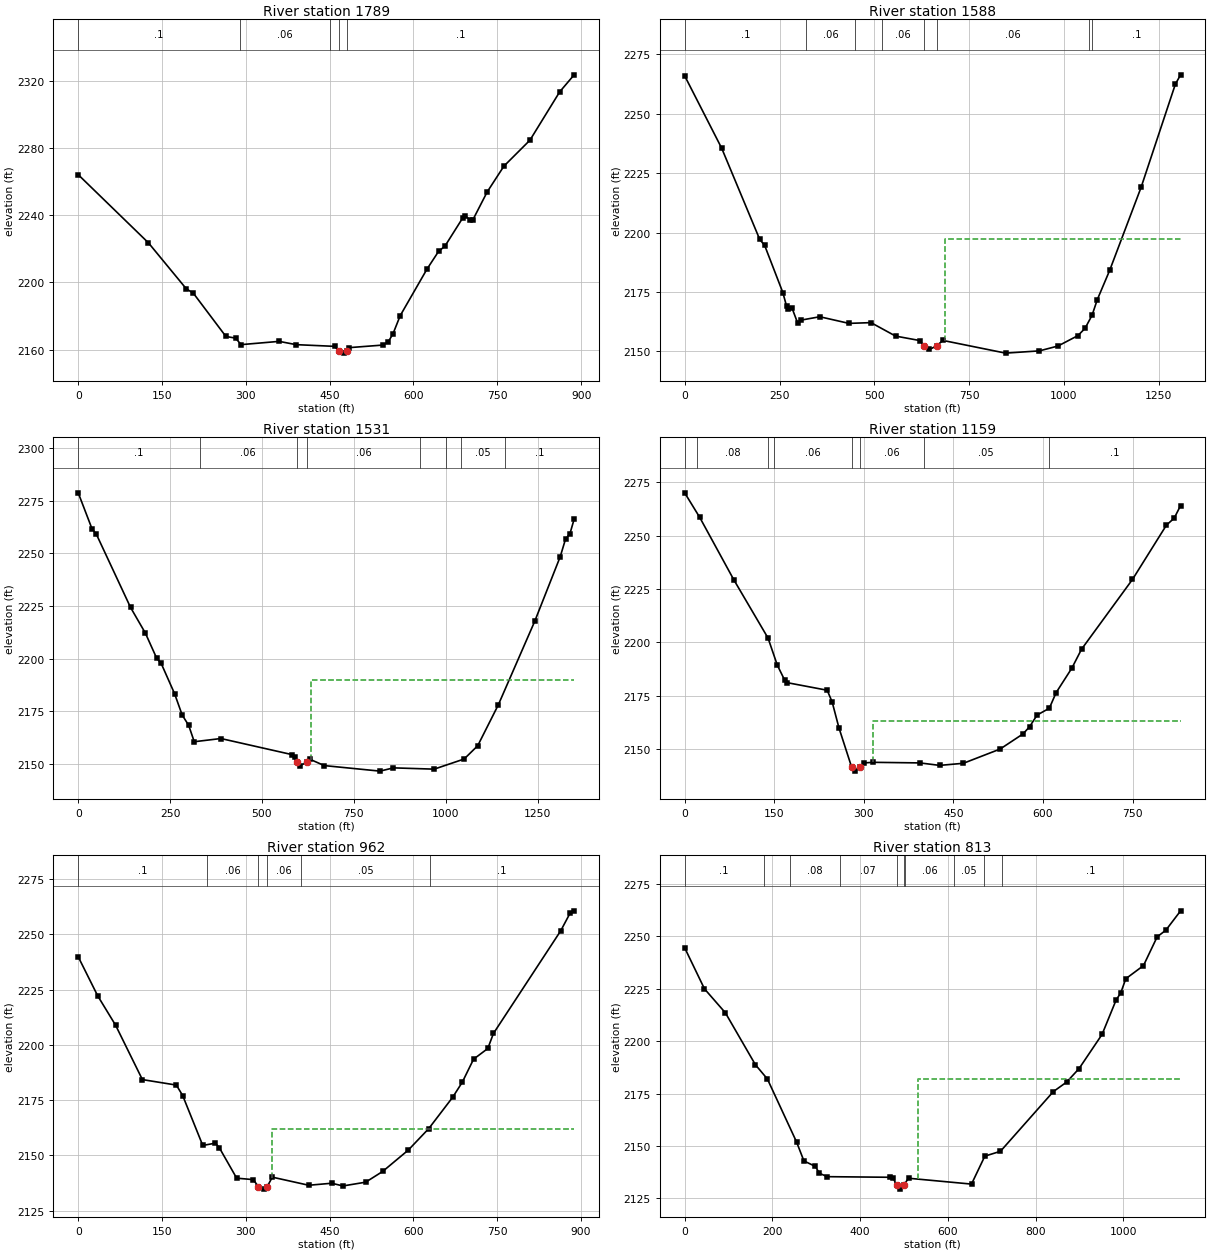
Type RM Length L Ch R = 1 ,1789    ,181.3,201.3,218.7
XS GIS Cut Line= 3
2309024.26523043687500.2969623362308489.92174919687722.225716576
2308355.62151593688000.351022319
#Sta/Elev= 30
       0 2264.03   125.7 2223.49   193.5 2196.14     206 2193.57   264.3 2167.84
   281.6 2166.86   291.5 2162.98   359.6 2164.92   389.9 2162.97   459.2 2161.95
  466.21    2159   476.5 2157.93   480.9 2158.97   485.2  2161.2   545.5 2162.73
   554.7 2164.61   563.2 2169.32   576.2  2180.2   624.1 2207.86     645 2218.48
   656.2 2221.51   688.5 2238.52     693 2239.47   701.8 2236.92   706.3 2237.22
   731.9 2253.79   761.8  2269.1   808.4 2284.54   861.7 2313.31   887.5 2323.39
#Mann= 5 ,-1,0
       0      .1       0     290     .06       0     450      .1       0
  466.21    .045       0   480.9      .1       0
Bank Sta=466.21,480.9
XS Rating Curve= 0 ,0
Exp/Cntr(USF)=0,0
Exp/Cntr=0.3,0.1

Type RM Length L Ch R = 1 ,1588    ,63.3,56.3,58.6
BEGIN DESCRIPTION:
Structure XS 3
END DESCRIPTION:
XS GIS Cut Line= 6
2309021.89111846  687486.93899052308599.96890562687668.512480105
2308575.82907753687510.0292608542308544.34234522687417.668179436
2308497.11224677687299.0681544342308099.32986203687535.218646695
#Sta/Elev= 30
       0 2265.93    97.7 2235.42   197.8 2197.11   210.9 2194.54   258.8 2174.73
   268.8 2168.89   271.9 2167.97   283.1 2168.15     298 2161.84   307.5 2163.15
   356.2 2164.55     433 2161.76   491.2 2162.07     556 2156.41   619.7 2154.54
     631 2152.24   645.3 2150.78   664.2 2152.28   680.6 2154.59     846 2149.24
   935.3 2150.19   984.3 2152.24  1036.7 2156.61  1055.4 2159.64    1074 2165.17
  1087.9 2171.78  1120.5 2184.08  1203.3    2219  1293.8 2262.49  1307.5 2266.35
#Mann= 8 ,-1,0
       0      .1       0     320     .06       0     450      .1       0
  519.33     .06       0     631    .045       0   664.2     .06       0
 1064.93     .05       0 1074.93      .1       0
#XS Ineff= 2 , 0
                          686.35         2197.45
Permanent Ineff=
       F       F
Bank Sta=631,664.2
XS Rating Curve= 0 ,0
Exp/Cntr(USF)=0,0
Exp/Cntr=0.3,0.1

Type RM Length L Ch R = 1 ,1531    ,385.7,372.7,351.7
BEGIN DESCRIPTION:
Structure XS 2
END DESCRIPTION:
XS GIS Cut Line= 6
2309010.03632177 687441.521289352308634.62670872687610.744507042
2308606.11805453687478.7370430892308577.60940034687422.959241419
2308503.23899812687225.8776755182308052.09976358687500.583241164
#Sta/Elev= 30
       0 2278.81    37.4 2261.78    49.5 2259.09   142.4 2224.34   182.6 2212.19
   213.3 2200.29   225.8 2197.72     262 2183.45   282.8 2173.27   300.6 2168.29
   315.7 2160.54   388.2 2162.06   580.6 2154.46   589.6 2153.23     594  2150.8
   603.5 2149.23   622.1 2150.69   631.3 2152.13   669.6  2149.2   821.1 2146.57
   857.5 2148.12   968.4 2147.51  1049.9 2152.32  1086.9 2158.63  1142.8    2178
    1242 2217.75  1311.4 2248.47  1325.8 2256.79    1338 2259.47  1349.3 2266.34
#Mann= 8 ,-1,0
       0      .1       0     330     .06       0     594    .045       0
   622.1     .06       0  931.09     .05       0 1001.09     .06       0
 1041.09     .05       0 1161.09      .1       0
#XS Ineff= 2 , 0
                          633.79         2189.72
Permanent Ineff=
       F       F
Bank Sta=594,622.1
XS Rating Curve= 0 ,0
Exp/Cntr(USF)=0,0
Exp/Cntr=0.3,0.1

Type RM Length L Ch R = 1 ,1159    ,198.1,196.3,194.2
BEGIN DESCRIPTION:
Structure XS 1
END DESCRIPTION:
XS GIS Cut Line= 2
2308623.71202992686933.0855261172307983.83533833687462.366246322
#Sta/Elev= 30
       0 2270.14    25.2 2258.63    82.1 2229.47   139.6 2202.06   155.1 2189.37
   167.4 2182.36   170.7 2181.22   238.6 2177.62   246.9 2172.15   258.3    2160
   279.7 2141.46   284.9 2139.71  294.092141.481   300.9 2143.56   315.1 2143.84
   393.9 2143.56   426.9  2142.4   466.6 2143.38   528.2 2150.06   566.5 2157.15
   577.5 2160.52   590.1 2165.99   610.6 2169.19   621.9 2176.48   648.3 2187.99
   664.5 2196.84   749.8 2229.55   806.7 2255.02   819.6 2258.25   830.4 2264.19
#Mann= 8 ,-1,0
       0      .1       0      20     .08       0     140      .1       0
     150     .06       0   279.7    .045       0  294.09     .06       0
     400     .05       0     610      .1       0
#XS Ineff= 2 , 0
                           316.1         2163.08
Permanent Ineff=
       F       F
Bank Sta=279.7,294.09
XS Rating Curve= 0 ,0
Exp/Cntr(USF)=0,0
Exp/Cntr=0.3,0.1

Type RM Length L Ch R = 1 ,962     ,150.1,149.8,149.3
BEGIN DESCRIPTION:
Structure XS 4
END DESCRIPTION:
XS GIS Cut Line= 4
 2308543.1045316686901.4627645462308313.14956509686905.382451475
2308232.24597649687019.1806041512307912.14565671687426.770382266
#Sta/Elev= 30
       0 2239.89    34.9  2222.2    66.9 2208.92   114.9 2184.29   175.7 2181.81
     187 2177.09     223 2154.48   245.5 2155.52   252.4 2153.55   283.7 2139.67
   313.7 2139.01   322.72135.679   332.8 2134.71   337.92135.621   347.5 2140.13
   412.8 2136.46   453.9 2137.38   473.9 2136.15   514.6 2137.85   545.1 2142.72
   590.9 2152.37   627.5 2162.09   670.2 2176.22   687.5 2183.05   707.8 2193.53
   733.3 2198.37   743.4 2205.18   863.9 2251.67   880.8 2259.73   887.9 2260.69
#Mann= 6 ,-1,0
       0      .1       0  229.99     .06       0   322.7    .045       0
   337.9     .06       0  399.61     .05       0  629.61      .1       0
#XS Ineff= 2 , 0
                          346.96         2162.08
Permanent Ineff=
       F       F
Bank Sta=322.7,337.9
XS Rating Curve= 0 ,0
Exp/Cntr(USF)=0,0
Exp/Cntr=0.3,0.1

Type RM Length L Ch R = 1 ,813     ,94.3,94.8,95.2
BEGIN DESCRIPTION:
Structure XS 3
END DESCRIPTION:
XS GIS Cut Line= 5
2308545.27890016686871.9581326782308273.26530574686793.113612556
2308166.82520358686848.3047766412307966.06098579687170.076893373
 2307715.3220591687411.997314822
#Sta/Elev= 30
       0 2244.49    45.1 2224.92    92.8 2213.49   161.3 2188.72   188.6 2181.93
     255 2151.94   271.9 2142.85     298 2140.24     307 2136.99     325 2135.35
   468.6 2135.06   474.9 2134.85  483.292131.295   489.9 2129.41  499.122131.201
   510.4  2134.6     654 2131.81   684.4 2145.14     720 2147.45   840.6 2175.92
   870.8 2180.44   899.1 2186.85   951.7 2203.19   983.9 2219.68   994.2 2222.92
  1005.8 2229.74  1046.1    2236  1077.3 2249.71  1097.1 2252.88  1130.8 2262.12
#Mann= 10 ,-1,0
       0      .1       0     180     .06       0     240     .08       0
  353.21     .07       0  483.29    .045       0  499.12     .07       0
  503.11     .06       0  613.11     .05       0  683.11     .06       0
  723.11      .1       0
#XS Ineff= 2 , 0
                          531.12         2182.07
Permanent Ineff=
       F       F
Bank Sta=483.29,499.12
XS Rating Curve= 0 ,0
Exp/Cntr(USF)=0,0
Exp/Cntr=0.3,0.1

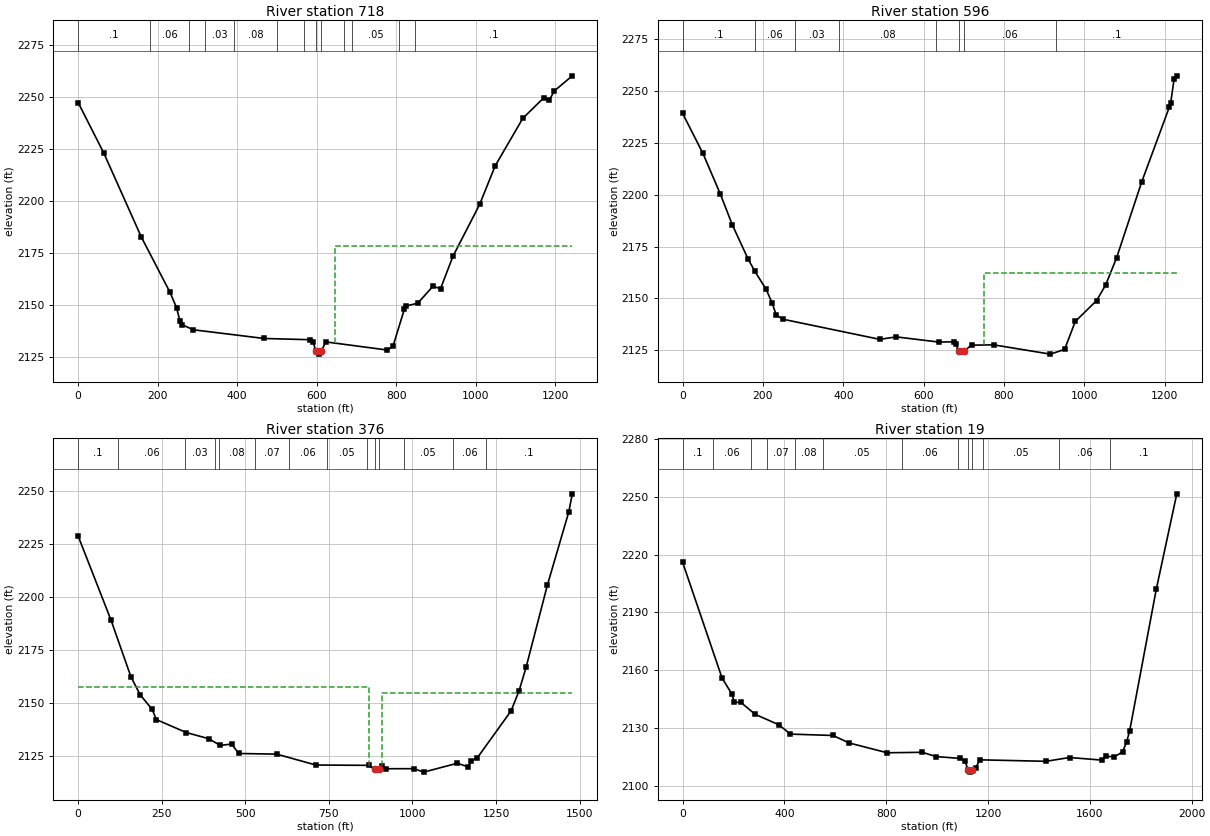
Type RM Length L Ch R = 1 ,718     ,120.2,121.8,123.4
BEGIN DESCRIPTION:
Structure XS 2
END DESCRIPTION:
XS GIS Cut Line= 6
2308576.81670821686832.5358726172308237.78527168686708.355753425
2308099.80736147686785.229160544 2307985.4828073686958.687104812
2307879.16415113687120.7036918612307666.13198034687362.666078942
#Sta/Elev= 30
       0 2247.53    64.6  2223.2     159 2182.83   230.7 2156.41   247.8 2148.77
   255.7 2142.68   260.5 2140.76     290 2138.24   468.2 2134.06   582.2 2133.48
   590.9 2132.41   598.3 2127.91   605.2 2126.54  611.412127.842   622.7 2132.42
   777.6 2128.51   791.9 2130.28   820.6 2148.19   825.4 2149.73   854.1    2151
   892.4 2159.16   911.5    2158   942.8  2173.6  1009.8 2198.49  1049.1 2217.12
  1118.5 2239.93  1171.7 2249.89  1185.3 2248.76  1197.9 2253.13  1242.9 2260.36
#Mann= 13 ,-1,0
       0      .1       0     180     .06       0     280     .08       0
     320     .03       0  391.06     .08       0  501.06     .07       0
  569.01     .06       0   598.3    .045       0  611.41     .06       0
  669.01     .07       0  689.01     .05       0  806.75     .06       0
  846.75      .1       0
#XS Ineff= 2 , 0
                          644.91         2178.48
Permanent Ineff=
       F       F
Bank Sta=598.3,611.41
XS Rating Curve= 0 ,0
Exp/Cntr(USF)=0,0
Exp/Cntr=0.3,0.1

Type RM Length L Ch R = 1 ,596     ,220,220.4,222.6
BEGIN DESCRIPTION:
Structure XS 1
END DESCRIPTION:
XS GIS Cut Line= 4
2308574.95553659686813.6767622752308120.38529745686629.007602626
2307782.61435588686939.9462731462307686.33385384687203.533877088
#Sta/Elev= 30
       0 2239.28    50.5 2220.02    93.7 2200.47   123.9 2185.44   162.7 2169.15
     180 2163.04   207.8 2154.46   223.2 2147.67   232.8  2142.1   249.1    2140
   490.6 2130.27   532.2 2131.44   638.1 2128.95   674.9 2129.08   679.9 2128.06
  687.432124.505  699.462124.498   719.3 2127.45   774.4 2127.61   915.5 2123.13
   951.1 2125.41   977.6 2138.88  1030.6 2148.96  1053.3  2156.5  1080.5 2169.62
  1142.7 2206.05  1211.5 2242.19  1215.1 2244.32  1223.6 2255.73  1230.4 2257.44
#Mann= 8 ,-1,0
       0      .1       0     180     .06       0     280     .03       0
     390     .08       0  630.65     .06       0  687.43    .045       0
  699.46     .06       0  930.65      .1       0
#XS Ineff= 2 , 0
                          750.04         2162.24
Permanent Ineff=
       F       F
Bank Sta=687.43,699.46
XS Rating Curve= 0 ,0
Exp/Cntr(USF)=0,0
Exp/Cntr=0.3,0.1

Type RM Length L Ch R = 1 ,376     ,355.4,357.3,357.3
XS GIS Cut Line= 4
2308613.39240889686762.6087460242307959.17360628 686533.12891988
2307717.61589455686688.1284515742307667.29137128 687183.32176062
#Sta/Elev= 30
       0 2228.89    98.8 2189.07   158.1 2162.49   185.6 2154.06   221.7 2147.15
   233.9 2142.39   323.4  2136.3   391.3 2133.34   425.2  2130.2   459.1 2130.88
   480.3 2126.41   593.8 2126.11   711.1 2120.98   869.2 2120.82     887 2118.91
   900.8 2118.94   908.2 2120.49   920.2 2119.23  1004.5 2119.26  1033.6 2117.63
  1134.1 2121.81  1166.3 2120.12  1174.4 2122.64  1194.5 2124.47    1295 2146.47
  1319.1 2156.02  1340.3 2167.25  1403.5 2205.68  1467.9 2240.38  1478.1 2248.75
#Mann= 14 ,-1,0
       0      .1       0     120     .06       0     320     .03       0
     410     .07       0     420     .08       0     530     .07       0
     630     .06       0   743.3     .05       0   863.3     .06       0
     887    .045       0   900.8     .06       0   973.3     .05       0
 1120.31     .06       0 1220.31      .1       0
#XS Ineff= 2 , 0
          871.05 2157.66  909.17          2154.9
Permanent Ineff=
       F       F
Bank Sta=887,900.8
XS Rating Curve= 0 ,0
Exp/Cntr(USF)=0,0
Exp/Cntr=0.3,0.1

Type RM Length L Ch R = 1 ,19      ,,,
XS GIS Cut Line= 4
2308623.24563982686722.5818497782307562.19343532 686378.49068259
2307521.54262968 686399.522717322307579.71632515687177.495410395
#Sta/Elev= 30
       0 2215.97   154.6    2156   192.5 2147.76   203.6 2143.32     229 2143.23
     285 2137.06   377.5 2131.65   423.7 2126.78     591 2126.07   652.9 2122.23
   803.7 2117.09   942.3 2117.34   994.3 2115.15  1088.1 2114.16  1108.6    2113
  1121.9 2108.07  1130.8 2107.04  1138.7 2108.08  1151.6  2109.2  1166.9 2113.43
  1427.6 2112.66    1520 2114.63  1648.2 2113.27  1664.3  2115.2  1696.4 2115.05
  1728.1 2117.48  1744.5 2122.76  1756.5 2128.65  1860.8    2202  1941.4 2251.55
#Mann= 13 ,-1,0
       0      .1       0     120     .06       0     270     .03       0
     330     .07       0     440     .08       0     550     .05       0
     860     .06       0 1080.75      .1       0  1121.9    .045       0
  1138.7      .1       0 1179.56     .05       0 1479.56     .06       0
 1679.56      .1       0
Bank Sta=1121.9,1138.7
XS Rating Curve= 0 ,0
Exp/Cntr(USF)=0,0
Exp/Cntr=0.3,0.1
LCMann Table=0

Chan Stop Cuts=-1
Use User Specified Reach Order=0
Composite Channel Slope=5